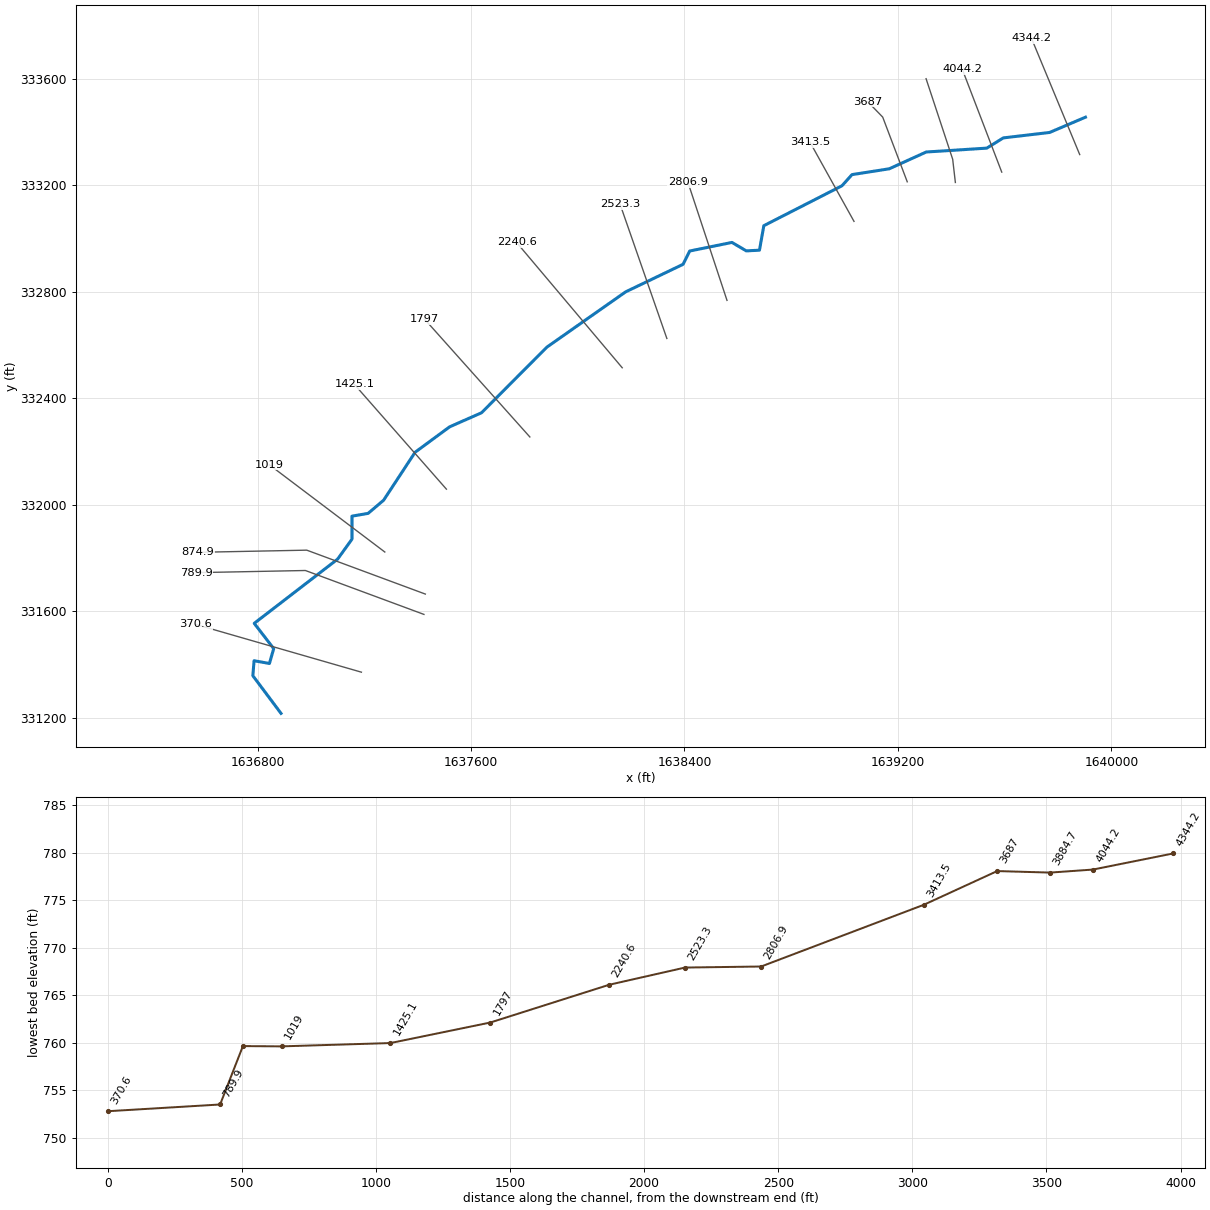
--- BROADRN.prj (project) ---

Proj Title=BROADRN
Current Plan=p01
Default Exp/Contr=0,0
English Units
Geom File=g01
Flow File=f01
Plan File=p01
BEGIN DESCRIPTION:
END DESCRIPTION:
DSS Export Rating Curves= 0
DSS Export Rating Curve Sorted= 0
DSS Export Volume Flow Curves= 0
DXF OffsetX= 0
DXF OffsetY= 0
DXF ScaleX= 0
DXF ScaleY= 0

--- BROADRN.p01 (plan) ---

Plan Title=Floodplain
Program Version=4.00
Geom File=g01
Flow File=f01
K Sum by GR=0
Std Step Tol=0.01
Critical Tol=0.01
Num of Std Step Trials=20
Max Error Tol=0.3
Flow Tol Ratio=0.001
Split Flow NTrial=30
Split Flow Tol=0.02
Split Flow Ratio=0.02
Log Output Level=0
Friction Slope Method=1
Unsteady Friction Slope Method=2
Unsteady Bridges Friction Slope Method=1
Global Log Level=0
CheckData=False
Run HTab=0
Run UNet=0
Run PostProcess=0
UNET Theta=0
UNET Theta Warmup=0
UNET ZTol=0
UNET ZSATol=0
UNET MxIter=0
UNET MaxInSteps=0
UNET DtIC=0
UNET DtMin=0
UNET MaxCRTS=0
UNET WFStab=0
UNET SFStab=0
UNET WFX=0
UNET SFX=0
UNET DSS MLevel=0
UNET DZMax Abort=0
UNET Convert EG Bridges=0
UNET Use Existing IB Tables=0
UNET Froude Limit=0
UNET Froude Power=0
Write IC File=0
Echo Input=False
Echo Output=False
Write Detailed=0

--- BROADRN.f01 (steady flow) ---

Flow Title=NFF Regression Equation
Program Version=4.10
Number of Profiles= 1
Profile Names=P100yr
River Rch & RM=BROADRN,Main            ,4344.2
1260.731
River Rch & RM=BROADRN,Main            ,2240.6
1305.342
River Rch & RM=BROADRN,Main            ,1797
1531.745
River Rch & RM=BROADRN,Main            ,1019
1545.471
River Rch & RM=BROADRN,Main            ,874.9
1546.267
Boundary for River Rch & Prof#=BROADRN,Main            , 1
Up Type= 0
Dn Type= 3
Dn Slope=0.00358
DSS Import GetInterval= 0
DSS Import GetPeak= 0
DSS Import FillOption= 0

--- BROADRN.g01 (geometry) ---

Geom Title=USGS 10m DEM
Program Version=4.10

River Reach=BROADRN         ,Main
Reach XY= 30
     1639902.969      333456.095     1639768.594      333398.803
     1639595.218      333378.461     1639533.177      333339.949
     1639306.094      333325.366     1639167.552      333262.345
     1639027.969       333240.47     1638990.306      333198.543
     1638697.381       333048.63     1638681.094      332956.616
     1638631.615      332954.012     1638577.969      332985.782
     1638419.603      332953.491     1638394.603      332903.491
     1638179.325      332800.019     1637884.186       332592.38
     1637639.279      332345.963     1637519.609      332293.032
     1637390.158      332197.526     1637272.214      332017.446
     1637214.105      331967.967     1637153.695      331957.611
     1637153.695       331871.31     1637099.613      331795.941
     1636787.206      331554.875     1636860.273      331459.945
     1636844.164      331404.137      1636786.63      331414.493
     1636782.027       331358.11     1636887.584       331216.73

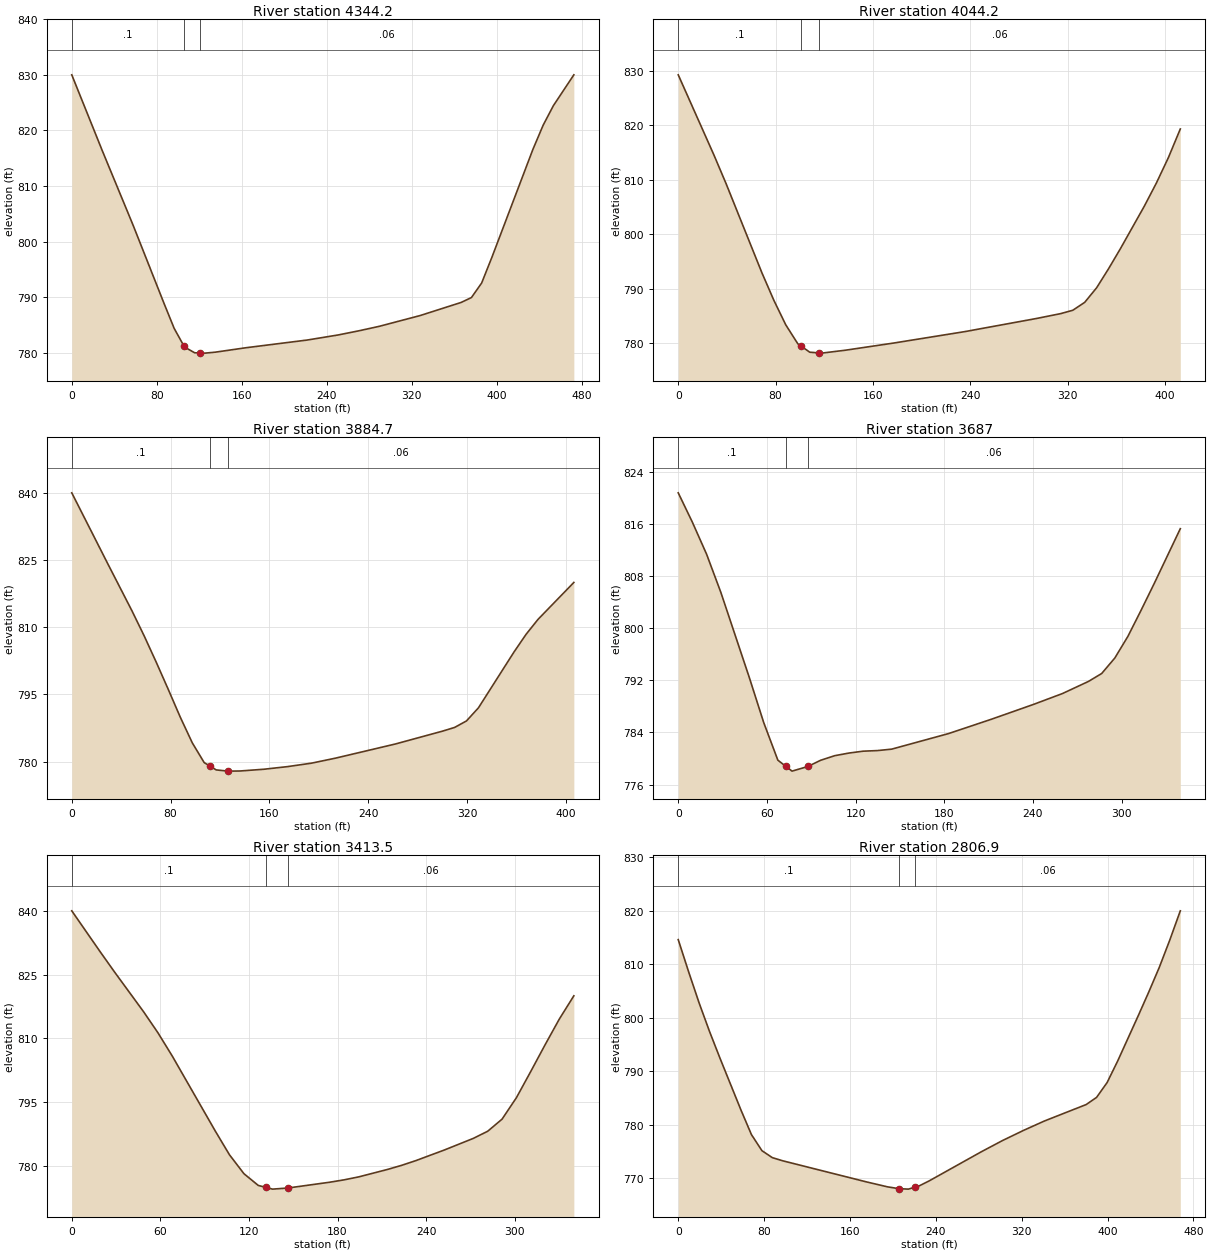
Type RM Length L Ch R = 1 ,4344.2  ,300.5,300,299.4
XS GIS Cut Line= 2
     1639881.502      333315.728     1639700.737      333752.395
#Sta/Elev= 25
       0     830    28.9  816.27    57.9  802.86    86.8  788.89    96.4  784.37
   105.8  781.12   106.1  781.02   115.7  779.98   120.8  779.95   125.4  779.92
     135  780.09     164  780.89   221.8  782.28   250.8  783.19   270.1  783.93
   289.4  784.74   327.9  786.68   366.5  789.04   376.2  789.92   385.8  792.53
   395.4  797.13     434  816.55   443.7  820.93   453.3  824.44   472.6     830
#Mann= 3 , 0 , 0
       0      .1       0   105.8    .045       0   120.8     .06       0
Bank Sta=105.8,120.8
XS Rating Curve= 0 ,0
Exp/Cntr=0.3,0.1

Type RM Length L Ch R = 1 ,4044.2  ,160.1,159.5,158.6
XS GIS Cut Line= 2
     1639589.188      333249.953     1639441.619       333635.37
#Sta/Elev= 25
       0  829.21    29.5  814.44    39.3  809.29    68.8  792.93    78.6   787.9
    88.4   783.4    98.3  779.93   101.1  779.49   108.1  778.39   116.1  778.25
   117.9  778.22   137.6  778.76   176.9  780.06   235.8  782.17   294.8  784.58
   314.4  785.46   324.3  786.07   334.1  787.52   343.9  790.19   353.7  793.67
   363.6  797.41   383.2  805.18     393  809.37   402.9  814.04   412.7  819.29
#Mann= 3 , 0 , 0
       0      .1       0   101.1    .045       0   116.1     .06       0
Bank Sta=101.1,116.1
XS Rating Curve= 0 ,0
Exp/Cntr=0.3,0.1

Type RM Length L Ch R = 1 ,3884.7  ,197.5,197.6,198.7
XS GIS Cut Line= 3
     1639415.399      333210.971     1639405.288       333298.32
     1639305.606      333600.738
#Sta/Elev= 27
       0     840    29.3  824.09    48.8  813.63    58.6  808.08    68.4  802.19
    78.2  796.08    87.9   789.9    97.6  784.19   107.2   779.8   111.8  779.03
   116.9  778.17   126.5   777.9   126.8   777.9   136.2  777.93   155.5  778.32
   174.8  778.91   194.1  779.68   213.4  780.79   261.6  783.93   300.2  786.83
   309.9  787.65   319.5   789.1   329.2  792.03   358.1  804.54   367.8  808.45
   377.4  811.76   406.4     820
#Mann= 3 , 0 , 0
       0      .1       0   111.8    .045       0   126.8     .06       0
Bank Sta=111.8,126.8
XS Rating Curve= 0 ,0
Exp/Cntr=0.3,0.1

Type RM Length L Ch R = 1 ,3687    ,269,273.5,275.7
XS GIS Cut Line= 3
     1639235.021      333213.495     1639143.007       333456.55
     1639087.452      333513.842
#Sta/Elev= 27
       0  820.74     9.6  816.22    19.2  811.32    28.9  805.43    48.1  792.41
    57.8  785.53    67.4  779.74    72.7  778.81      77  778.06    87.7  778.77
    96.3  779.72   105.9  780.43   115.5  780.83   125.1  781.12   134.8  781.21
   144.4  781.43   182.9  783.82   211.8  786.01   240.6  788.31   259.9  789.95
   277.6  791.82   286.5  793.03   295.4  795.41   304.2  798.71   313.1   802.7
     322  806.81   339.7  815.24
#Mann= 3 , 0 , 0
       0      .1       0    72.7    .045       0    87.7     .06       0
Bank Sta=72.7,87.7
XS Rating Curve= 0 ,0
Exp/Cntr=0.3,0.1

Type RM Length L Ch R = 1 ,3413.5  ,611,606.6,597.2
XS GIS Cut Line= 2
     1639035.432      333064.819     1638870.564      333362.111
#Sta/Elev= 28
       0     840    19.4  830.29    29.1  825.54    48.6  816.27    58.3  811.33
      68  805.86    97.1  788.23   106.8  782.59   116.6  778.14   126.3  775.38
   131.3  774.93     136  774.51   146.3  774.77   174.8  776.14   184.5   776.7
   194.3  777.39   213.7  779.13   223.4  780.11   233.1  781.23   252.5  783.74
     272  786.46   281.7  788.14   291.4  790.98   301.1  796.02   310.8  802.18
   320.5  808.46   330.2  814.55     340     820
#Mann= 3 , 0 , 0
       0      .1       0   131.3    .045       0   146.3     .06       0
Bank Sta=131.3,146.3
XS Rating Curve= 0 ,0
Exp/Cntr=0.3,0.1

Type RM Length L Ch R = 1 ,2806.9  ,283,283.6,284.4
XS GIS Cut Line= 2
     1638559.392      332768.045     1638412.676      333212.205
#Sta/Elev= 30
       0  814.62     9.8  808.54    19.5  802.77    29.2  797.44      39  792.42
    58.5  782.76    68.2   778.2      78  775.19    87.7  773.89    97.4   773.3
   175.4  769.36   194.9  768.44   205.4   768.1   214.4  768.01   220.4  768.36
   224.1  768.57   233.9  769.56   282.6  775.01   302.1  777.08   321.6  778.97
   341.1  780.73   380.1  783.81   389.8  785.15   399.6  787.92   409.3  791.88
   428.8  800.49   438.5  804.87   448.3  809.48     458  814.54   467.8     820
#Mann= 3 , 0 , 0
       0      .1       0   205.4    .045       0   220.4     .06       0
Bank Sta=205.4,220.4
XS Rating Curve= 0 ,0
Exp/Cntr=0.3,0.1

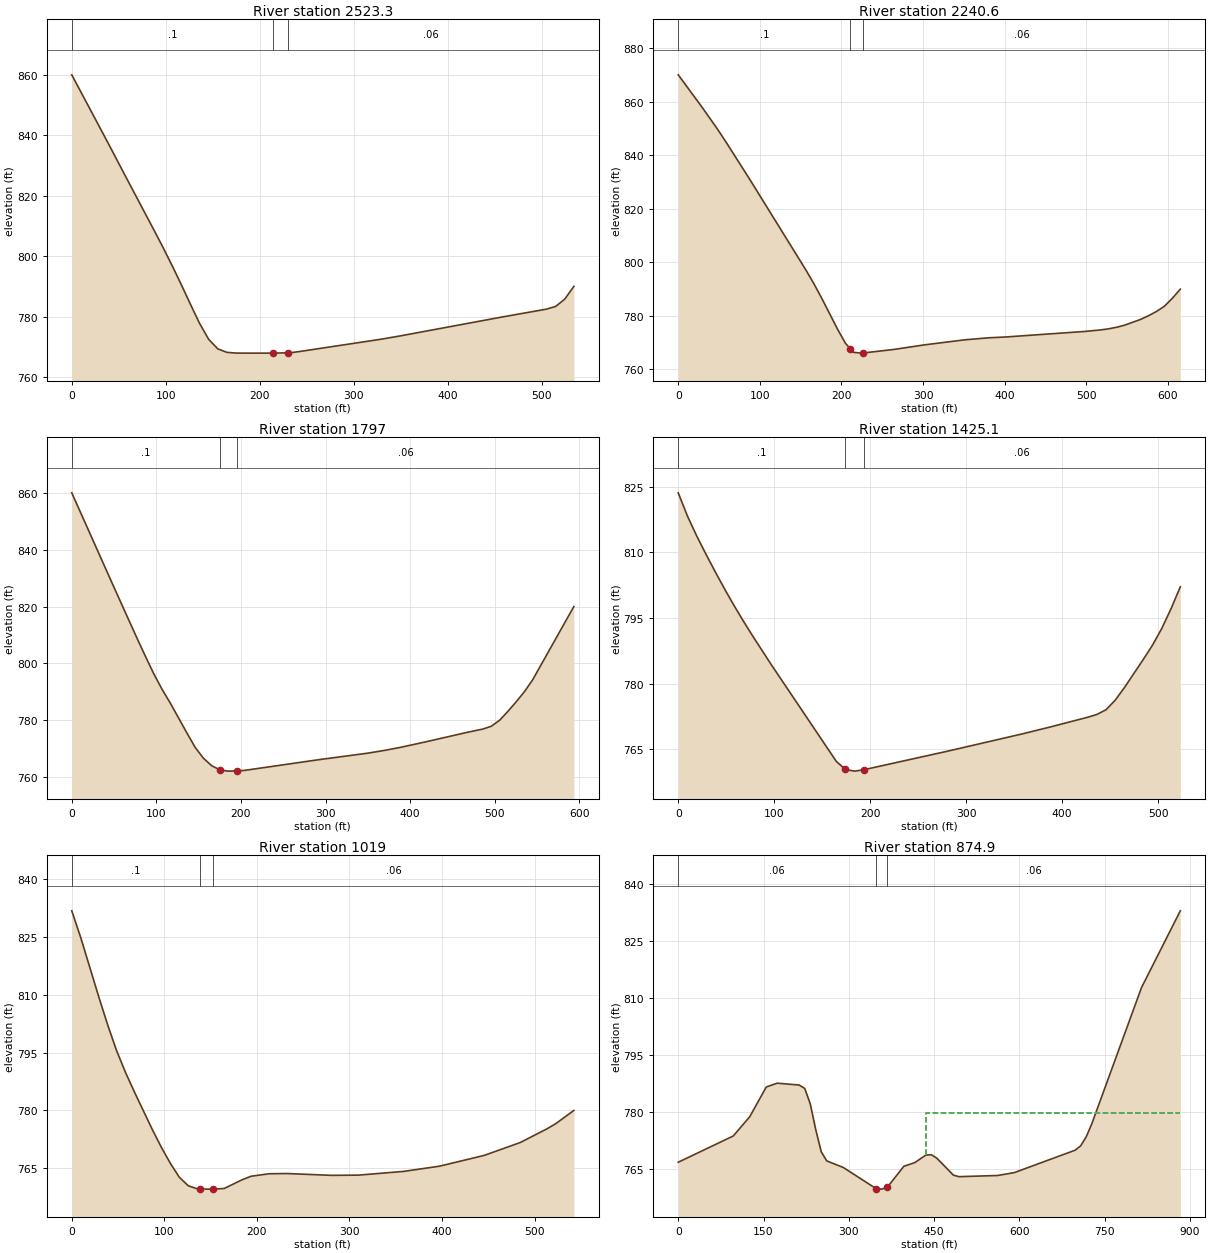
Type RM Length L Ch R = 1 ,2523.3  ,274.3,282.7,290.7
XS GIS Cut Line= 2
     1638333.937      332624.996     1638158.518      333129.287
#Sta/Elev= 25
       0     860    38.8  837.32    58.2  825.81    87.4  808.63    97.1  802.84
   106.8  796.82   116.5  790.54   126.2  784.08   135.9  777.75   145.6  772.46
   155.3  769.31     165  768.16   174.7  767.92   184.4   767.9   214.5   767.9
   229.5     768     233  768.05   242.7  768.45   330.1  772.56   349.5  773.61
   456.3  779.78   504.8  782.46   514.5  783.34   524.2  785.76   533.9  789.99
#Mann= 3 , 0 , 0
       0      .1       0   214.5    .045       0   229.5     .06       0
Bank Sta=214.5,229.5
XS Rating Curve= 0 ,0
Exp/Cntr=0.3,0.1

Type RM Length L Ch R = 1 ,2240.6  ,442.9,443.6,444
XS GIS Cut Line= 2
     1638166.616      332514.958     1637770.658      332985.657
#Sta/Elev= 30
       0     870    29.3  857.86    48.8  849.41    58.6  844.87    87.9  830.84
   156.2  797.23     166  792.12   175.7  786.64   195.3  774.96     205  769.72
     211  767.68   214.8  766.38   224.6  766.09     226  766.13   263.6  767.44
   302.7  769.22   351.5  771.07   380.8  771.82   400.3   772.1   497.9  774.18
   517.5  774.76   527.2  775.16     537  775.74   546.8  776.52   566.3  778.66
     576  780.03   585.8  781.63   595.6  783.59   605.3  786.55   615.1  789.98
#Mann= 3 , 0 , 0
       0      .1       0     211    .045       0     226     .06       0
Bank Sta=211,226
XS Rating Curve= 0 ,0
Exp/Cntr=0.3,0.1

Type RM Length L Ch R = 1 ,1797    ,372.1,372,371.4
XS GIS Cut Line= 2
     1637820.349      332255.057     1637425.347      332697.965
#Sta/Elev= 30
       0     860    48.6  827.64    68.1  814.79    77.8  808.44    87.6  802.15
    97.3  796.14     107  790.76   116.8  785.87   136.2  775.48   145.9  770.46
   155.7  766.63   165.4  764.02   175.1  762.54   184.8  762.11   195.1  762.17
   204.3  762.37   291.9  766.13   350.2  768.44   369.7   769.4   389.2  770.51
   418.3   772.4     467  775.72   486.4  776.94   496.2  777.94   505.9  780.05
   515.6  783.15   525.4  786.51   535.1  790.06   544.8  794.22   593.5     820
#Mann= 3 , 0 , 0
       0      .1       0   175.1    .045       0   195.1     .06       0
Bank Sta=175.1,195.1
XS Rating Curve= 0 ,0
Exp/Cntr=0.3,0.1

Type RM Length L Ch R = 1 ,1425.1  ,394.9,406.1,403.1
XS GIS Cut Line= 2
     1637507.591      332058.981     1637162.804      332452.392
#Sta/Elev= 28
       0  823.66     9.7  818.29    19.4  813.72    29.1  809.52    38.8  805.48
    48.4  801.61    58.1  797.88    67.8  794.32    77.5  790.91    96.9  784.34
   164.7  762.18   173.7  760.42   174.4  760.28   184.1  759.95   193.8  760.29
   280.9  764.53   358.4  768.47   387.5  770.05   426.2  772.26   435.9   772.9
   445.6  773.98   455.3  776.19     465  779.12   484.4  785.47     494  788.74
   503.7  792.57   513.4  797.11   523.1  802.14
#Mann= 3 , 0 , 0
       0      .1       0   173.7    .045       0   193.8     .06       0
Bank Sta=173.7,193.8
XS Rating Curve= 0 ,0
Exp/Cntr=0.3,0.1

Type RM Length L Ch R = 1 ,1019    ,134,144.1,160.9
XS GIS Cut Line= 2
     1637276.688       331822.87     1636844.184      332150.342
#Sta/Elev= 30
       0  831.74     9.7   824.8    29.1   809.5    38.8  802.17    48.4  795.52
    58.1  789.83    67.8  784.73    87.2  774.96    96.9   770.4   106.6  766.26
   116.2  762.68   125.9  760.46   135.6  759.69   138.1  759.67   145.3   759.6
   153.1   759.6   164.7  759.77   184.1  762.03   193.8  762.94   213.1  763.58
   232.5  763.64   280.9  763.17     310  763.23   358.4  764.19   397.2  765.54
   445.6  768.34   484.4  771.66   513.4  775.22   523.1  776.59   542.5     780
#Mann= 3 , 0 , 0
       0      .1       0   138.1    .045       0   153.1     .06       0
Bank Sta=138.1,153.1
XS Rating Curve= 0 ,0
Exp/Cntr=0.3,0.1

Type RM Length L Ch R = 1 ,874.9   ,86.2,85,83.9
XS GIS Cut Line= 3
     1637428.598      331664.883     1636984.153      331829.814
     1636575.289      331821.708
#Sta/Elev= 30
       0  766.71    96.8  773.63   125.8  778.71   154.8  786.52   174.1  787.53
   212.8  787.04   222.5  786.14   232.2  782.08   241.9  775.26   251.5  769.48
   261.2  767.06   290.2  765.34   348.3  759.73     358  759.63   367.7  760.11
   396.7  765.64     416  766.61   435.4  768.59     445  768.69   454.7   767.8
   483.8  763.33   493.5  762.91   561.7  763.22   590.9  763.97     698  769.88
   707.7  771.02   717.5  773.39   727.2  776.78   814.8  812.72     883  832.92
#Mann= 3 , 0 , 0
       0     .06       0   348.3    .045       0   367.7     .06       0
#XS Ineff= 2 , 0
                             435           779.6
Permanent Ineff=
       F       F
Bank Sta=348.3,367.7
XS Rating Curve= 0 ,0
Exp/Cntr=0.3,0.1

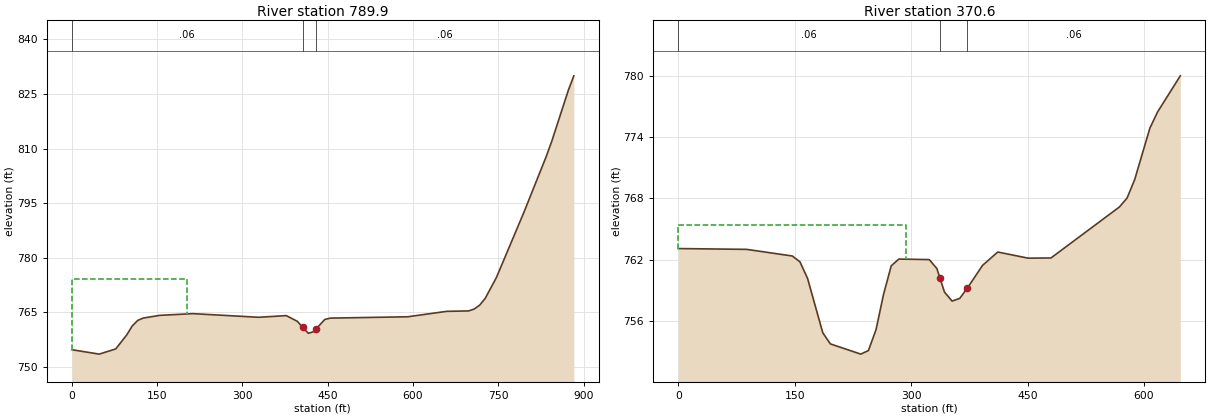
Type RM Length L Ch R = 1 ,789.9   ,415.5,419.3,408.7
XS GIS Cut Line= 3
     1637423.389      331588.495     1636978.945      331753.425
      1636570.08      331745.319
#Sta/Elev= 30
       0   754.7    48.4  753.48    77.4  754.92    96.8  758.78   106.4  761.24
   116.1  762.75   125.8   763.4   154.8  764.14   212.8  764.61   328.9  763.61
   377.3  764.07   396.7   762.5   406.3  760.82     416  759.21   425.7  759.67
     430  760.47     445  763.01   454.7  763.38   590.9  763.75   659.1  765.24
     698  765.36   707.7  765.87   717.5  766.96   727.2  768.83   746.7   774.5
   795.4  792.55   834.3  807.76   844.1  811.97   873.3  826.02     883     830
#Mann= 3 , 0 , 0
       0     .06       0   406.3    .045       0     430     .06       0
#XS Ineff= 2 , 0
          203.32  774.23
Permanent Ineff=
       F       F
Bank Sta=406.3,430
XS Rating Curve= 0 ,0
Exp/Cntr=0.3,0.1

Type RM Length L Ch R = 1 ,370.6   ,341.7,370.6,397.2
XS GIS Cut Line= 2
     1637189.014      331371.481     1636567.596      331550.955
#Sta/Elev= 30
       0   763.1    88.2  763.02     147  762.37   156.8   761.8   166.6  760.18
   186.2  754.86     196  753.77   235.2  752.77     245  753.12   254.8  755.16
   264.6  758.65   274.4  761.41   284.2  762.07   323.4  762.02   333.2  761.14
   337.3  760.18     343  758.84   352.8  757.96   362.6  758.22   372.4  759.22
     392  761.45   411.6  762.76   450.8  762.16   480.2  762.18   568.4  767.17
   578.2  768.04     588  769.84   607.6  774.88   617.4  776.45   646.8     780
#Mann= 3 , 0 , 0
       0     .06       0   337.3    .045       0   372.4     .06       0
#XS Ineff= 2 , 0
          293.55   765.4
Permanent Ineff=
       F       F
Bank Sta=337.3,372.4
XS Rating Curve= 0 ,0
Exp/Cntr=0.3,0.1

Chan Stop Cuts=-1
Use User Specified Reach Order=0
Composite Channel Slope=5